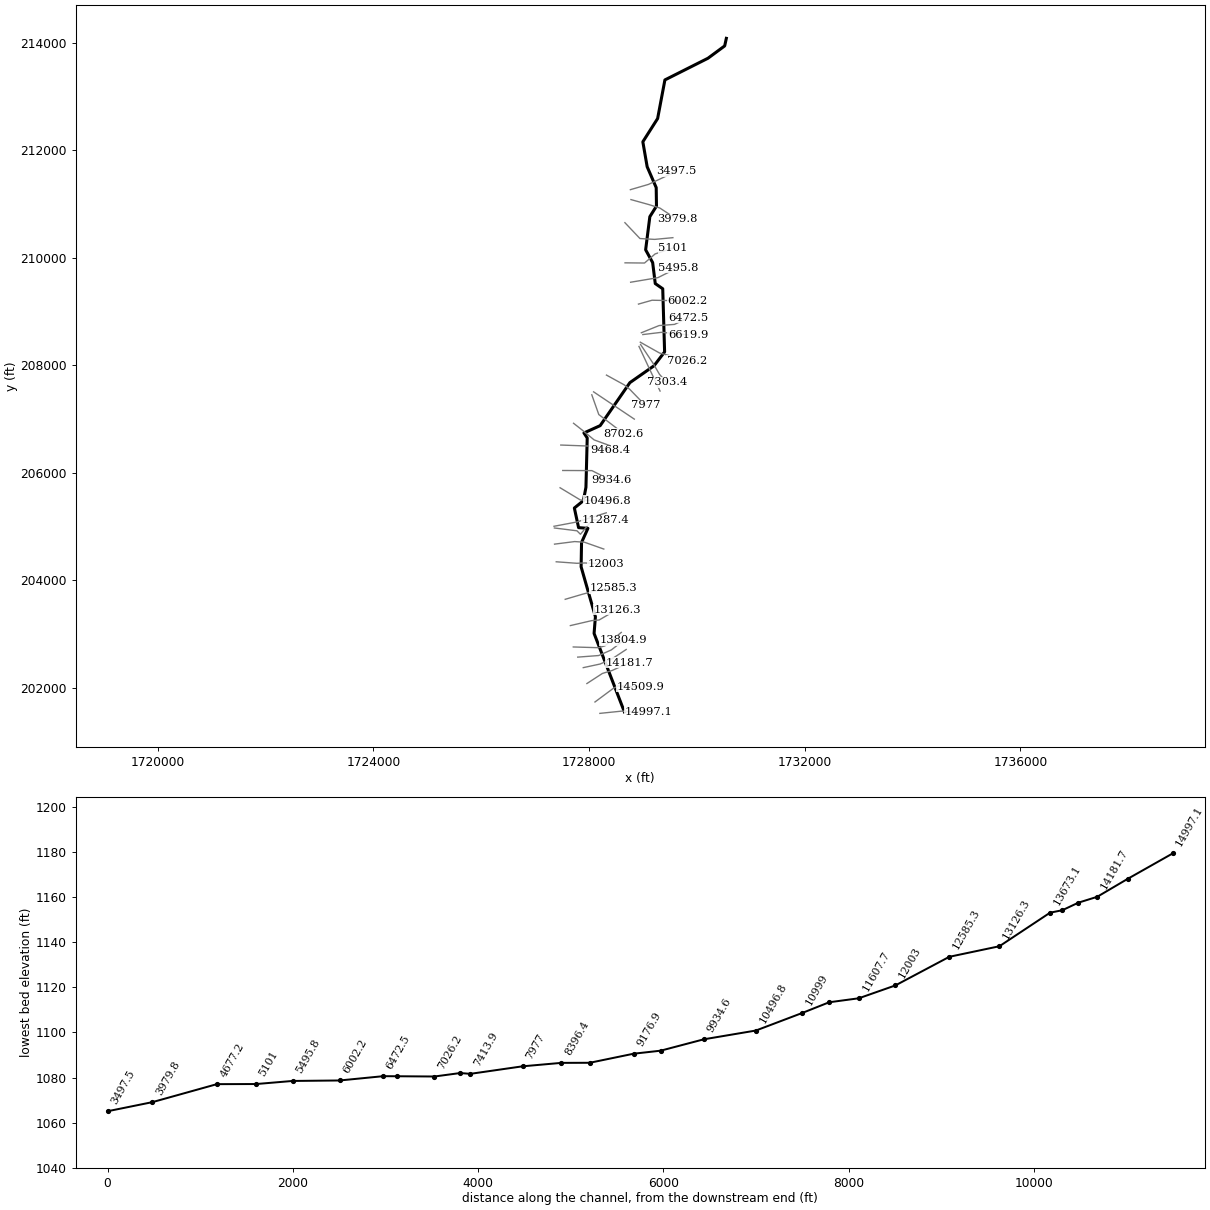
--- LitleCbCr1.prj (project) ---

Proj Title=LitleCbCr1
Current Plan=p01
Default Exp/Contr=0,0
English Units
Geom File=g01
Flow File=f01
Plan File=p01
BEGIN DESCRIPTION:
END DESCRIPTION:
DSS Export Rating Curves= 0
DSS Export Rating Curve Sorted= 0
DSS Export Volume Flow Curves= 0
DXF OffsetX= 0
DXF OffsetY= 0
DXF ScaleX= 0
DXF ScaleY= 0

--- LitleCbCr1.p01 (plan) ---

Plan Title=Floodplain
Program Version=4.00
Geom File=g01
Flow File=f01
K Sum by GR=0
Std Step Tol=0.01
Critical Tol=0.01
Num of Std Step Trials=20
Max Error Tol=0.3
Flow Tol Ratio=0.001
Split Flow NTrial=30
Split Flow Tol=0.02
Split Flow Ratio=0.02
Log Output Level=0
Friction Slope Method=1
Unsteady Friction Slope Method=2
Unsteady Bridges Friction Slope Method=1
Global Log Level=0
CheckData=False
Run HTab=0
Run UNet=0
Run PostProcess=0
UNET Theta=0
UNET Theta Warmup=0
UNET ZTol=0
UNET ZSATol=0
UNET MxIter=0
UNET MaxInSteps=0
UNET DtIC=0
UNET DtMin=0
UNET MaxCRTS=0
UNET WFStab=0
UNET SFStab=0
UNET WFX=0
UNET SFX=0
UNET DSS MLevel=0
UNET DZMax Abort=0
UNET Convert EG Bridges=0
UNET Use Existing IB Tables=0
UNET Froude Limit=0
UNET Froude Power=0
Write IC File=0
Echo Input=False
Echo Output=False
Write Detailed=0

--- LitleCbCr1.f01 (steady flow) ---

Flow Title=NFF Regression Equation
Program Version=4.00
Number of Profiles=1
Profile Names=P100yr
River Rch & RM=LitleCbCr1,Main      ,14997.1
615.0533
River Rch & RM=LitleCbCr1,Main      ,13673.1
663.7560
River Rch & RM=LitleCbCr1,Main      ,11607.7
720.9213
River Rch & RM=LitleCbCr1,Main      ,11287.4
877.5069
River Rch & RM=LitleCbCr1,Main      ,9468.4
891.0336
River Rch & RM=LitleCbCr1,Main      ,9176.9
1205.276
River Rch & RM=LitleCbCr1,Main      ,6472.5
1318.181
River Rch & RM=LitleCbCr1,Main      ,4677.2
1406.802
River Rch & RM=LitleCbCr1,Main      ,185.3
1504.719
Boundary for River Rch & Prof#=LitleCbCr1,Main      ,1
Up Type=0
Dn Type=3
Dn Slope=0.029194

--- LitleCbCr1.g01 (geometry) ---

Geom Title=USGS 10m DEM
Program Version=4.00

River Reach=LitleCbCr1      ,Main
Reach XY= 30
     1728655.556      201552.276     1728092.931      203013.041
     1728117.571      203323.799      1727852.37      204251.949
     1727860.314      204704.177     1727978.424      204967.722
     1727805.225      204980.943     1727726.992      205345.585
     1727894.689      205482.032     1727941.845      205731.474
     1727965.644      206649.034      1727904.78      206741.693
     1728205.654      206877.996     1728757.063      207678.003
      1729204.67      207991.246     1729400.819      208249.172
     1729366.168      209423.614     1729227.541       209520.42
     1729179.138      209910.743      1729049.03      210148.112
     1729126.863      210764.187        1729250.      210961.284
     1729244.966      211305.527     1729077.298       211693.14
     1728997.142      212157.422     1729271.298      212589.953
     1729406.439      213308.255     1730204.897      213711.356
     1730514.887      213940.928     1730545.811      214081.834

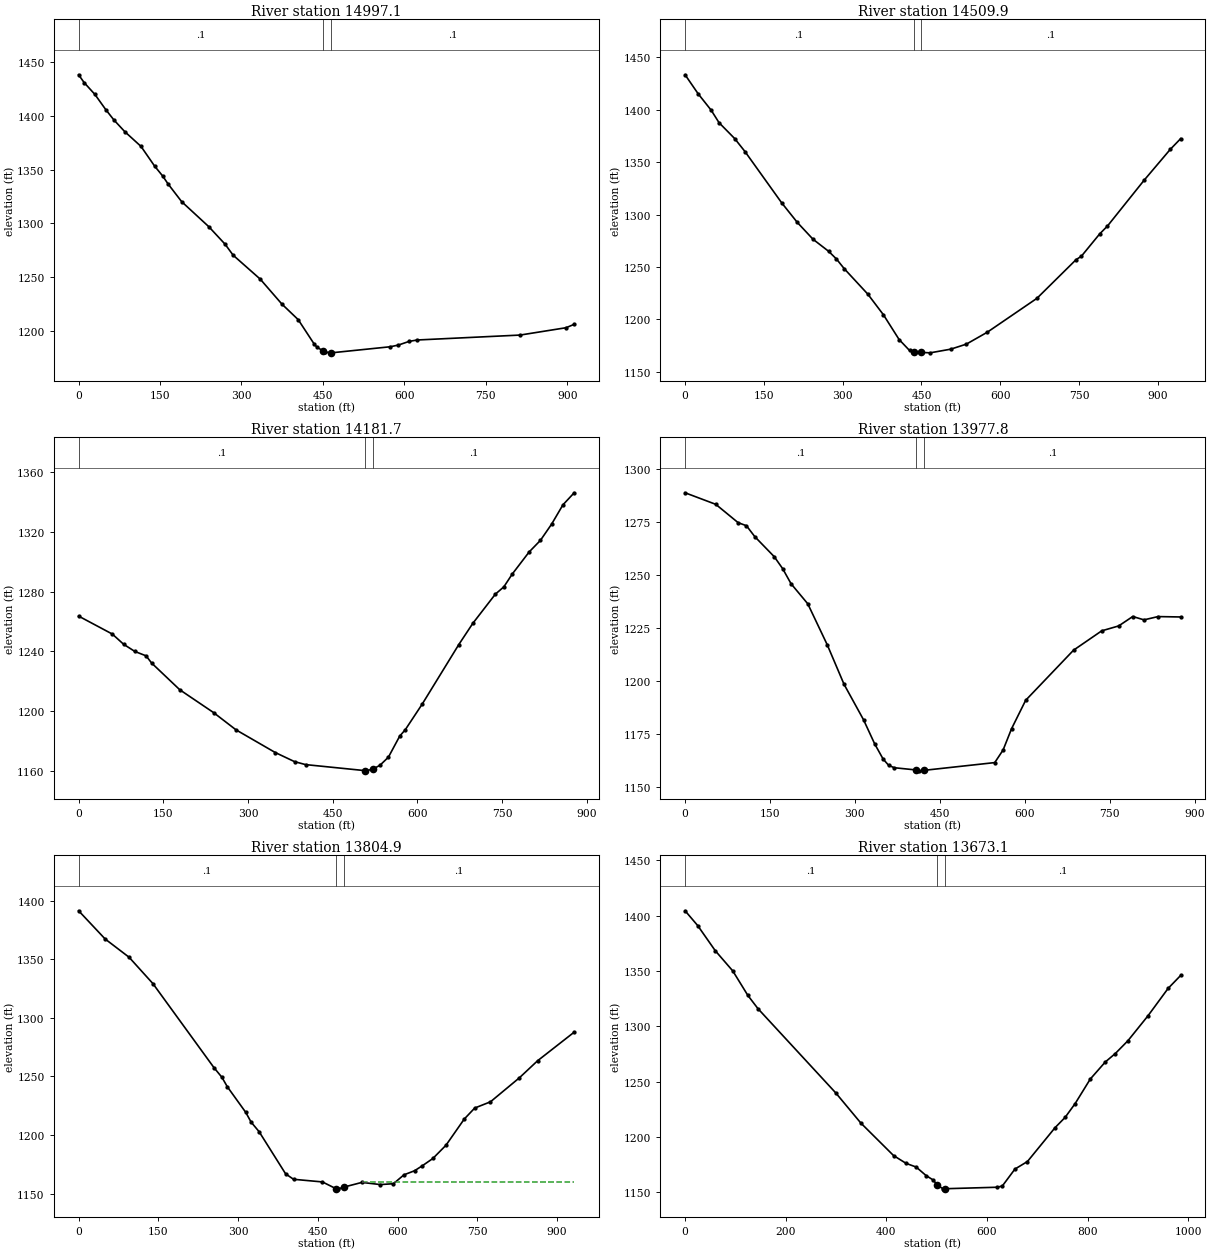
Type RM Length L Ch R = 1 ,14997.1 ,475,487.2,499.3
XS GIS Cut Line= 4
      1728200.17      201526.071     1728602.524      201567.729
     1728756.882      201560.292     1729110.415       201547.69
#Sta/Elev= 30
       0 1438.53      10 1431.33      30 1420.21    49.9  1406.1    64.9 1396.46
    84.9 1385.57   114.9 1371.75   139.8 1353.52   154.8 1344.17   164.8 1336.73
   189.8 1320.24   239.7 1296.95   269.7 1280.63   284.6 1270.35   334.6 1247.99
   374.5 1224.72   404.5 1210.23   434.4 1187.12   439.4 1184.45   450.2 1181.16
   454.4 1180.05   464.3 1179.31   465.2 1179.31     574 1184.98   588.9 1186.55
   608.9    1190   623.8 1191.29   813.2 1195.88   897.8 1202.72   912.8 1205.89
#Mann= 3 , 0 , 0
       0      .1       0   450.2    .045       0   465.2      .1       0
Bank Sta=450.2,465.2
XS Rating Curve= 0 ,0
Exp/Cntr=0.3,0.1

Type RM Length L Ch R = 1 ,14509.9 ,332.6,328.2,324.2
XS GIS Cut Line= 4
     1728109.449      201737.957     1728444.036      201987.429
      1728535.02      202035.856     1728957.655      202021.181
#Sta/Elev= 30
       0 1433.49    24.8 1415.38    49.7 1399.63    64.6 1387.76    94.4 1372.58
   114.3 1359.98   183.8 1311.26   213.6 1292.53   243.5 1276.47   273.3 1264.92
   288.2 1257.56   303.1 1248.25   347.8 1224.07   377.6 1204.31   407.4 1180.71
   427.2 1170.29   434.8 1168.59   449.8 1168.44   466.4 1168.01   505.7 1171.52
   535.4 1176.32   575.2 1187.68   669.7 1220.04   744.3    1257   754.3 1260.22
   789.1  1281.5     804 1289.08   873.7 1332.76   923.4 1362.18   943.3  1372.5
#Mann= 3 , 0 , 0
       0      .1       0   434.8    .045       0   449.8      .1       0
Bank Sta=434.8,449.8
XS Rating Curve= 0 ,0
Exp/Cntr=0.3,0.1

Type RM Length L Ch R = 1 ,14181.7 ,201.7,203.9,205.7
XS GIS Cut Line= 4
     1727959.766      202080.925     1728247.393      202268.763
     1728429.361      202324.527     1728741.935      202468.341
#Sta/Elev= 30
       0  1263.6    59.7 1251.59    79.7 1244.76    99.6 1239.96   119.5 1237.02
   129.4 1232.17   179.2 1214.32     239 1199.07   278.8 1187.51   348.4 1172.32
   382.6 1166.22   402.1 1164.25   506.6 1160.25   509.4 1160.08   521.6 1161.32
   533.8 1163.79   548.8 1169.22   568.8 1183.29   578.7 1187.59   608.6 1204.68
   673.5 1244.57   698.4 1258.79   738.3  1278.3   753.3 1283.17   768.2 1291.74
   798.1 1306.51   818.1 1314.27     838 1325.18     858 1338.06   877.9 1346.12
#Mann= 3 , 0 , 0
       0      .1       0   506.6    .045       0   521.6      .1       0
Bank Sta=506.6,521.6
XS Rating Curve= 0 ,0
Exp/Cntr=0.3,0.1

Type RM Length L Ch R = 1 ,13977.8 ,172.2,172.9,173.5
XS GIS Cut Line= 4
     1727892.409       202376.74     1728205.395      202444.194
     1728426.644      202541.328     1728688.365       202714.01
#Sta/Elev= 30
       0 1288.63    54.2 1283.18    93.6 1274.55   108.4 1273.08   123.1 1267.95
   157.6 1258.45   172.4 1252.82   187.2 1245.72   216.7 1236.27   251.2 1216.88
   280.8 1198.28   315.2 1181.57     335 1170.14   349.8 1163.04   359.6 1160.07
   369.5 1158.94   407.9 1157.89   413.9 1157.47   422.9 1157.73     547 1161.36
   561.8 1167.32   576.7 1177.33   601.6 1190.73   686.2 1214.38     736 1223.51
   765.9 1225.82   790.8 1230.26   810.7 1228.69   835.5 1230.23   875.4 1230.05
#Mann= 3 , 0 , 0
       0      .1       0   407.9    .045       0   422.9      .1       0
Bank Sta=407.9,422.9
XS Rating Curve= 0 ,0
Exp/Cntr=0.3,0.1

Type RM Length L Ch R = 1 ,13804.9 ,135.3,131.9,128.5
XS GIS Cut Line= 4
     1727789.511      202572.324      1728177.82      202601.828
     1728412.899      202706.519      1728638.46      202881.638
#Sta/Elev= 30
       0 1391.41    49.9 1367.32    94.9 1351.76   139.8 1329.24   254.6 1257.55
   269.6  1249.3   279.6 1241.35   314.5 1219.33   324.5 1211.07   339.5 1202.93
   389.4 1166.95   404.3 1162.28   458.7 1160.02   483.8 1154.36   488.4 1154.13
   498.8 1155.59   532.9 1159.62   567.6 1157.77   592.3 1158.51   612.1  1166.1
   631.9 1169.54   646.8 1173.87   666.5 1180.05   691.1 1191.33   725.5 1213.68
   745.2 1223.08   774.8 1228.39   828.9 1248.75   863.4  1263.4   932.3 1287.82
#Mann= 3 , 0 , 0
       0      .1       0   483.8    .045       0   498.8      .1       0
#XS Ineff= 2 , 0
                          532.82         1159.63
Permanent Ineff=
       F       F
Bank Sta=483.8,498.8
XS Rating Curve= 0 ,0
Exp/Cntr=0.3,0.1

Type RM Length L Ch R = 1 ,13673.1 ,551.7,546.8,541.8
XS GIS Cut Line= 4
     1727707.015      202761.369     1728171.084      202747.586
     1728292.885      202781.338     1728597.142      203032.241
#Sta/Elev= 30
       0 1404.39      25 1391.04    59.9 1368.34    94.8 1350.01   124.8 1327.86
   144.8 1315.94   299.5 1239.75   349.4 1212.49   414.4 1183.12   439.3 1176.07
   459.3 1172.76   478.9 1165.09   493.4 1160.95   500.9 1156.54   512.9 1153.05
   515.9 1153.14   620.6  1154.5   630.6 1155.65   655.6 1170.91   680.5 1177.75
   735.4 1208.35   755.4 1217.65   775.4 1230.18   805.3 1252.24   835.3 1267.75
   855.2 1275.37   880.2 1286.92   920.1 1309.46   960.1 1334.23     985 1345.91
#Mann= 3 , 0 , 0
       0      .1       0   500.9    .045       0   515.9      .1       0
Bank Sta=500.9,515.9
XS Rating Curve= 0 ,0
Exp/Cntr=0.3,0.1

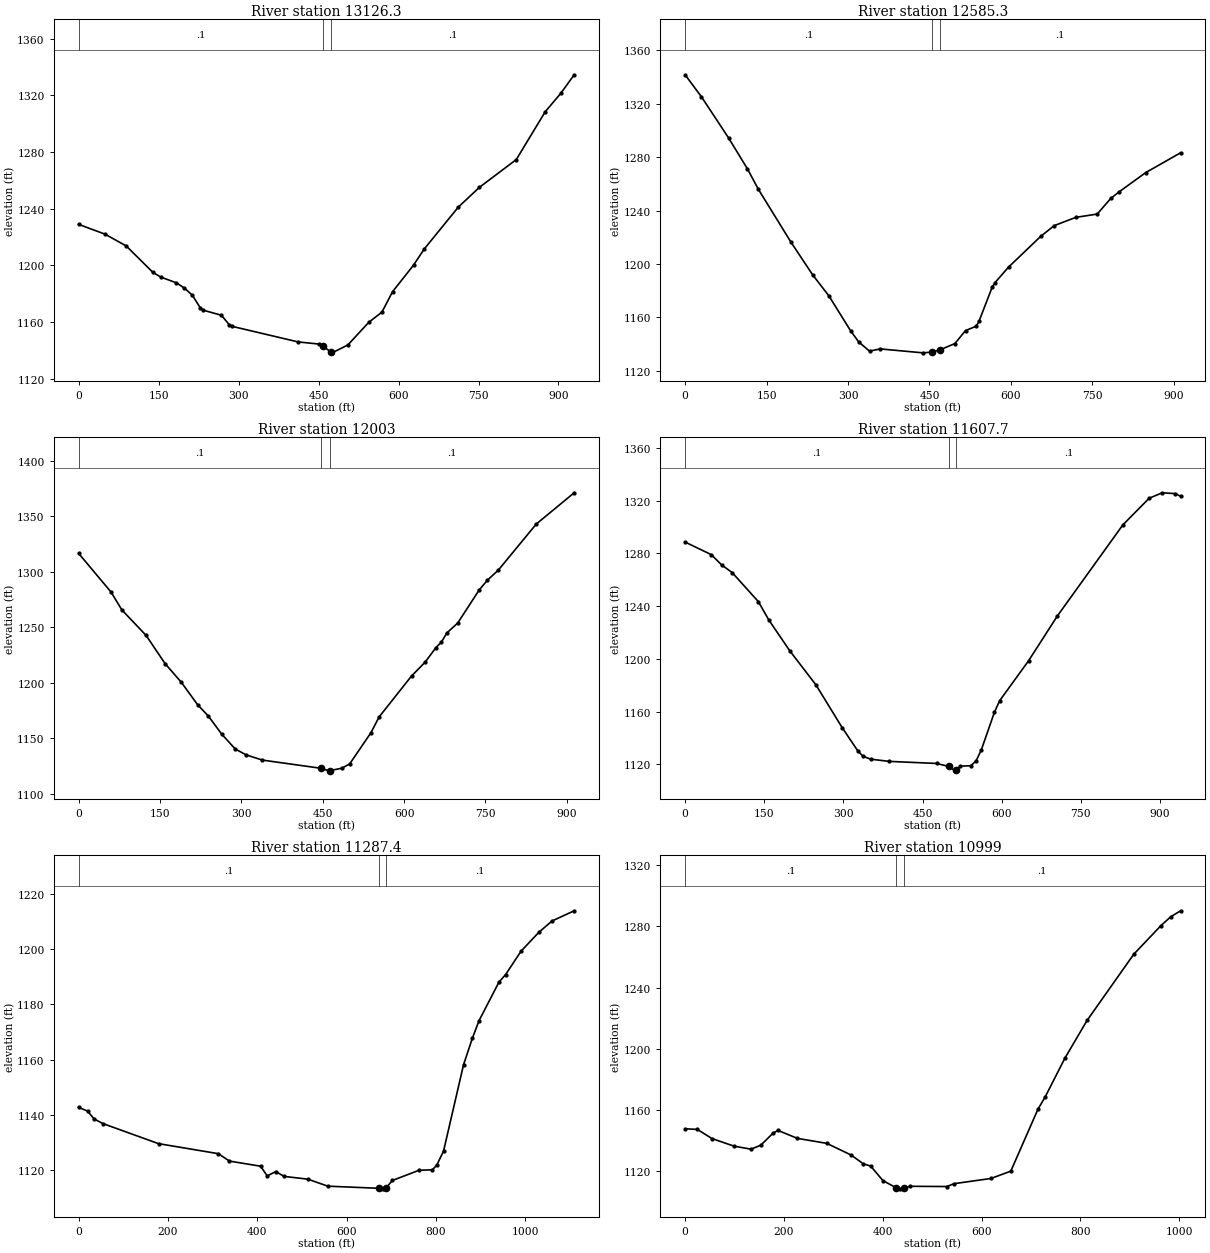
Type RM Length L Ch R = 1 ,13126.3 ,536.9,541,545.2
XS GIS Cut Line= 4
     1727653.145      203158.864     1728049.213      203251.175
     1728186.263      203262.595     1728518.719       203457.23
#Sta/Elev= 30
       0 1228.85    49.6 1221.92    89.3 1213.61   138.9 1195.11   153.8 1191.69
   183.5 1187.56   198.4 1183.88   213.3 1178.82   228.1 1169.99   233.1 1168.34
   267.8  1164.7   282.7 1157.94   287.6 1156.89   411.6 1145.89   450.9 1144.37
   459.2 1142.67   474.2 1138.42   475.4 1138.18   504.9 1143.72   544.2 1159.73
   568.9 1166.94   588.7 1181.29   628.2 1200.11   647.9 1211.33   712.1 1241.03
   751.6 1254.96   820.8 1274.58   875.1 1308.34   904.8 1321.57   929.4 1334.43
#Mann= 3 , 0 , 0
       0      .1       0   459.2    .045       0   474.2      .1       0
Bank Sta=459.2,474.2
XS Rating Curve= 0 ,0
Exp/Cntr=0.3,0.1

Type RM Length L Ch R = 1 ,12585.3 ,587.2,582.2,577.2
XS GIS Cut Line= 4
      1727557.39      203647.734     1727873.657      203741.206
     1728077.887      203795.305      1728445.44      203849.504
#Sta/Elev= 30
       0 1341.75      30 1325.33      80  1294.5   114.9 1271.22   134.9 1256.01
   194.9 1216.43   234.8 1191.98   264.8 1176.17   304.8 1150.02   319.8 1141.64
   339.6 1134.79   359.3 1136.44   437.9  1133.5   454.3 1134.04   469.3 1135.72
   496.8 1140.44   516.5 1150.19   536.2 1153.46   541.1 1156.98   565.8 1182.96
   570.8 1186.11   595.6 1197.68     655 1220.77   679.8 1228.78   719.4 1234.94
     759 1237.45   783.8  1249.1   798.7 1253.89   848.2 1268.47   912.6 1283.35
#Mann= 3 , 0 , 0
       0      .1       0   454.3    .045       0   469.3      .1       0
Bank Sta=454.3,469.3
XS Rating Curve= 0 ,0
Exp/Cntr=0.3,0.1

Type RM Length L Ch R = 1 ,12003   ,397.7,395.3,392.9
XS GIS Cut Line= 4
     1727390.901      204345.728     1727773.395      204317.795
     1727918.676      204323.665     1728303.061       204307.44
#Sta/Elev= 30
       0 1316.61    59.8 1281.78    79.7 1265.72   124.5 1242.68   159.4 1217.36
   189.3 1200.57   219.2 1180.46   239.1 1170.16     264 1153.74   288.9 1140.43
   308.8 1135.19   338.7  1130.5   447.7 1123.06   461.1 1120.82   462.7    1121
   485.3 1123.19   499.8 1127.13   538.9 1155.13   553.9  1169.3   613.8 1206.23
   638.8 1218.65   658.8 1231.83   668.8 1236.68   678.8 1244.96   698.8 1253.84
   738.8  1283.9   753.8 1292.53   773.7 1301.51   843.7 1343.02   913.6 1371.18
#Mann= 3 , 0 , 0
       0      .1       0   447.7    .045       0   462.7      .1       0
Bank Sta=447.7,462.7
XS Rating Curve= 0 ,0
Exp/Cntr=0.3,0.1

Type RM Length L Ch R = 1 ,11607.7 ,321.2,320.3,340.6
XS GIS Cut Line= 4
     1727359.432       204673.95     1727733.294      204721.631
     1727912.431      204710.126     1728273.214      204582.562
#Sta/Elev= 30
       0 1288.59    49.6 1279.06    69.4 1271.21    89.3 1265.42   138.8 1243.45
   158.7 1229.48   198.4 1206.13     248 1180.27   297.6 1147.92   327.3 1130.26
   337.2 1126.15   352.1 1123.94   386.9 1122.29   476.6 1120.72   499.2 1118.48
   511.5 1115.12   514.2 1116.01   521.5 1118.64   541.4 1119.01   551.4 1122.64
   561.4 1131.03   586.2 1159.55   596.2 1168.36   650.8 1198.51   705.5 1232.55
   829.7 1301.66   879.4  1321.8   904.3 1325.96   929.1  1325.3   939.1 1323.29
#Mann= 3 , 0 , 0
       0      .1       0   499.2    .045       0   514.2      .1       0
Bank Sta=499.2,514.2
XS Rating Curve= 0 ,0
Exp/Cntr=0.3,0.1

Type RM Length L Ch R = 1 ,11287.4 ,281.7,288.5,274.4
XS GIS Cut Line= 5
     1727356.987      204974.435     1727775.765      204921.844
     1727840.043      204857.566     1728062.093      205126.364
     1728309.465      205116.625
#Sta/Elev= 30
       0  1142.8    19.9 1141.47    34.8  1138.6    54.6 1136.93   178.8 1129.69
   312.8 1126.06   337.6 1123.38   407.2 1121.54   422.1 1118.03   441.2 1119.57
   460.3 1117.84     513 1116.85   557.8 1114.31   673.3 1113.54   682.3 1113.35
   688.3 1113.69   702.2 1116.37     762 1120.07   791.9 1120.23   801.8 1121.96
   816.8    1127   861.6 1158.24   881.4 1167.83   896.3 1174.18   940.8 1188.06
   955.7 1190.81   990.4 1199.29    1030 1206.08  1059.7  1210.2  1109.2 1213.88
#Mann= 3 , 0 , 0
       0      .1       0   673.3    .045       0   688.3      .1       0
Bank Sta=673.3,688.3
XS Rating Curve= 0 ,0
Exp/Cntr=0.3,0.1

Type RM Length L Ch R = 1 ,10999   ,512.9,502.1,494.8
XS GIS Cut Line= 3
     1727349.286      205006.006     1727776.734      205086.998
     1728318.925      205256.368
#Sta/Elev= 30
       0 1147.84    24.7 1147.46    54.4 1141.47    98.9 1136.52   133.5 1134.54
   153.3 1137.15     178 1144.99   187.9 1146.78   227.4 1141.59   286.7 1138.34
   336.2  1130.7   360.9 1124.95   375.7 1123.51   400.4 1114.02   427.6 1109.31
     435 1108.64   442.6 1109.11     455  1110.3   529.7 1110.14   544.7 1112.02
   619.4 1115.43   659.3  1120.2   714.1 1160.51     729 1168.73   768.9 1194.01
   813.7 1218.59   908.4  1261.9   963.2 1280.48   983.2 1286.31  1003.1 1290.19
#Mann= 3 , 0 , 0
       0      .1       0   427.6    .045       0   442.6      .1       0
Bank Sta=427.6,442.6
XS Rating Curve= 0 ,0
Exp/Cntr=0.3,0.1

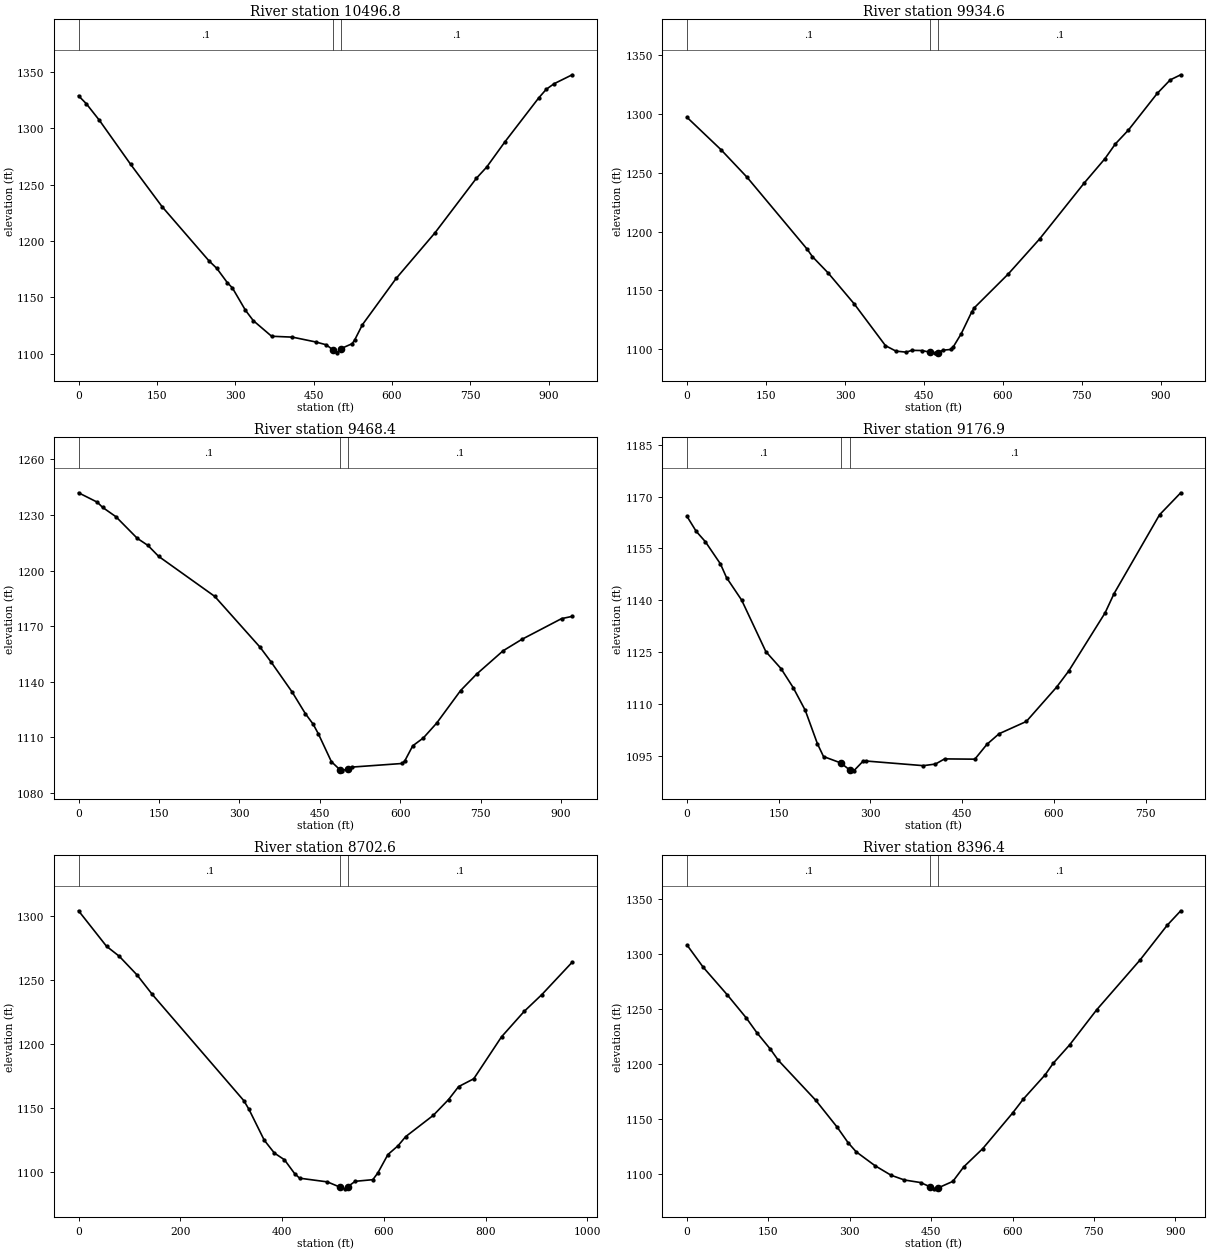
Type RM Length L Ch R = 1 ,10496.8 ,561.5,562.2,562.9
XS GIS Cut Line= 3
      1727462.26      205722.749     1727838.238      205495.435
     1728343.343      205477.645
#Sta/Elev= 30
       0 1328.84      15 1321.73    39.9  1307.1    99.8 1267.96   159.8 1230.55
   249.6 1182.45   264.6 1175.77   284.6 1163.18   294.6 1158.32   319.5 1138.57
   334.5 1129.38   369.5 1115.54   409.4 1114.76   454.2 1110.45     474 1107.97
   487.7  1103.2   493.9 1100.83   502.7 1104.66   523.6 1108.94   528.5 1112.24
   543.4 1125.85   607.8  1166.8   682.2 1207.29   761.4 1255.65   781.2 1265.62
   815.9 1287.89   880.4 1326.75   895.2 1334.61   910.1 1339.51   944.8 1347.46
#Mann= 3 , 0 , 0
       0      .1       0   487.7    .045       0   502.7      .1       0
Bank Sta=487.7,502.7
XS Rating Curve= 0 ,0
Exp/Cntr=0.3,0.1

Type RM Length L Ch R = 1 ,9934.6  ,466.8,466.2,465.5
XS GIS Cut Line= 3
     1727511.727      206043.793     1728052.447      206041.383
     1728406.589      205861.374
#Sta/Elev= 30
       0 1297.13    64.5 1269.66   114.1 1246.17   228.2 1185.07   238.1 1178.76
   267.9 1164.94   317.5 1138.62     377 1103.04   396.9  1098.4   416.7 1097.51
   426.6 1099.05   446.5  1098.9   461.7 1097.43   471.3 1096.94   476.7 1097.13
   486.2 1099.21     501  1099.8     506 1102.16   520.9 1113.18   540.7 1131.59
   545.7 1135.21   610.2 1163.95   669.8 1193.74   754.3 1241.17     794 1262.04
   813.8 1274.58   838.7 1286.42   893.3 1317.52   918.1 1329.05     938 1333.37
#Mann= 3 , 0 , 0
       0      .1       0   461.7    .045       0   476.7      .1       0
Bank Sta=461.7,476.7
XS Rating Curve= 0 ,0
Exp/Cntr=0.3,0.1

Type RM Length L Ch R = 1 ,9468.4  ,307.9,291.5,237.2
XS GIS Cut Line= 4
      1727475.33      206517.147     1727883.567       206502.21
     1728058.812       206496.27     1728387.341      206420.321
#Sta/Elev= 30
       0 1241.98    34.9 1236.92    44.8 1234.13    69.8 1229.05   109.6 1217.39
   129.5 1213.56   149.5 1207.65   254.1 1186.06   338.8 1158.58   358.7 1150.88
   398.6 1134.41   423.1 1122.81   437.7  1117.1   447.5 1111.84   471.8 1096.82
   487.3 1092.61   491.3  1091.9   502.3 1093.06   510.8 1093.94   603.7 1095.87
   608.6 1097.23   623.5  1105.4   643.4 1109.68   668.2 1117.68   712.8 1135.24
   742.5 1144.06   792.1  1156.7   826.8 1162.82   901.2 1174.06     921 1175.27
#Mann= 3 , 0 , 0
       0      .1       0   487.3    .045       0   502.3      .1       0
Bank Sta=487.3,502.3
XS Rating Curve= 0 ,0
Exp/Cntr=0.3,0.1

Type RM Length L Ch R = 1 ,9176.9  ,473.9,474.3,470.2
XS GIS Cut Line= 4
     1727712.177      206921.915     1727891.316      206780.689
     1728093.203      206612.923     1728390.821      206503.923
#Sta/Elev= 30
       0 1164.23    14.9 1159.94    29.8 1156.96    54.6 1150.49    64.5 1146.54
    89.3 1140.01   128.9 1125.09   153.7 1120.17   173.6 1114.67   193.4 1108.07
   213.2 1098.43   223.2  1094.7   251.3 1092.86   266.3 1090.78   272.7 1090.56
   287.6  1093.3   292.5 1093.41   386.6 1092.06   406.4 1092.53   421.3 1094.02
   470.8 1093.94   490.6 1098.25   510.4  1101.3     555 1104.86   604.5  1114.8
   624.3 1119.46   683.8  1136.3   698.6 1141.92   772.9 1164.72   807.6  1171.1
#Mann= 3 , 0 , 0
       0      .1       0   251.3    .045       0   266.3      .1       0
Bank Sta=251.3,266.3
XS Rating Curve= 0 ,0
Exp/Cntr=0.3,0.1

Type RM Length L Ch R = 1 ,8702.6  ,304.8,306.3,307.8
XS GIS Cut Line= 3
     1728050.339       207451.63     1728180.404      207083.993
     1728640.958      206730.777
#Sta/Elev= 30
       0 1304.03      55 1276.28      80 1268.48     115 1253.84     145 1238.58
     325 1155.47     335 1148.74     365 1124.62     385 1114.51   404.8 1109.27
   424.7 1098.51   434.6 1094.87   489.2 1091.97   514.3 1087.81   523.9 1086.54
   529.3 1088.22   543.8 1092.43   578.5 1093.71   588.4 1099.01   608.2 1113.39
   628.1 1120.26     643 1127.36   697.5 1144.08   727.3 1156.35   747.1  1166.5
   776.9 1172.63   831.5 1205.46   876.1 1225.37   910.8  1238.5   970.4 1263.81
#Mann= 3 , 0 , 0
       0      .1       0   514.3    .045       0   529.3      .1       0
Bank Sta=514.3,529.3
XS Rating Curve= 0 ,0
Exp/Cntr=0.3,0.1

Type RM Length L Ch R = 1 ,8396.4  ,421.4,419.4,417.3
XS GIS Cut Line= 3
     1728083.644      207506.588     1728461.367      207252.915
      1728839.09      206999.241
#Sta/Elev= 30
       0 1308.26    29.7 1288.14    74.2 1262.96   108.8  1242.2   128.6 1228.61
   153.3 1213.75   168.2 1203.44   237.4 1166.96     277 1142.41   296.7 1128.57
   311.6 1120.25   346.2 1107.64   375.9 1098.91   400.6 1094.55   430.3 1092.23
   447.5 1088.46     455  1086.5   462.5 1087.28     490 1093.31     510  1106.5
     545 1123.08     600 1155.44     620 1168.25     660 1190.21     675 1200.79
     705 1217.36     755 1249.37     835 1294.72     885  1326.3     910 1339.49
#Mann= 3 , 0 , 0
       0      .1       0   447.5    .045       0   462.5      .1       0
Bank Sta=447.5,462.5
XS Rating Curve= 0 ,0
Exp/Cntr=0.3,0.1

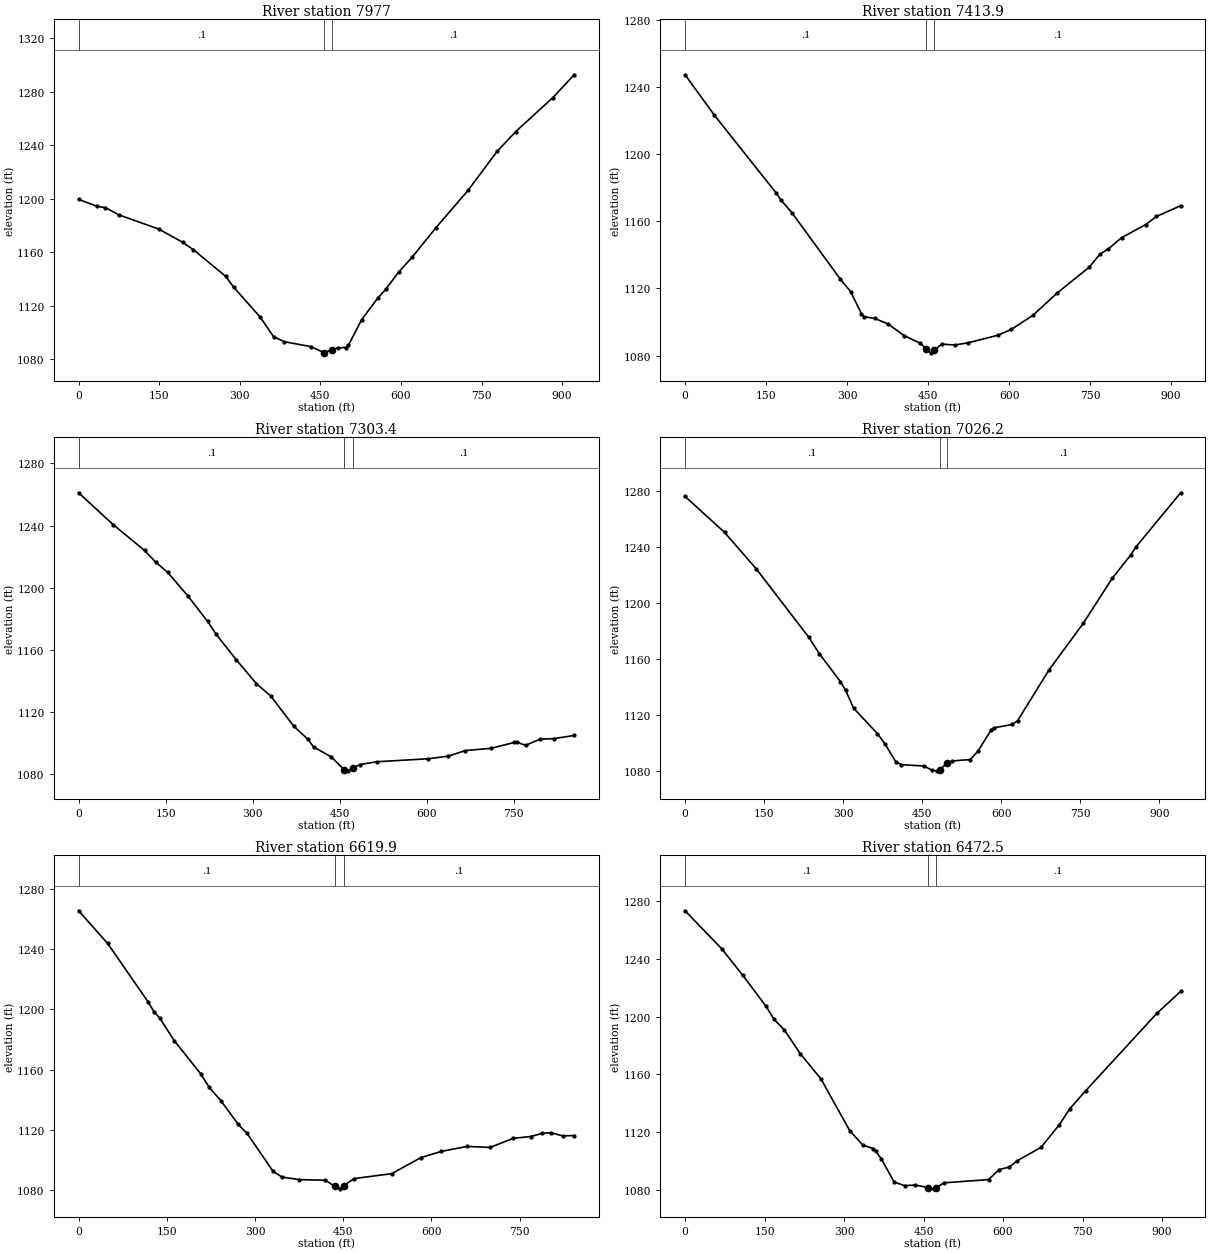
Type RM Length L Ch R = 1 ,7977    ,573.1,563.1,553.2
XS GIS Cut Line= 4
     1728322.659      207818.203     1728653.369      207635.629
     1728753.839      207554.116     1729042.387      207255.476
#Sta/Elev= 30
       0 1199.57    34.8 1194.26    49.7 1193.46    74.6 1188.01   149.1 1177.41
   193.8 1167.45   213.7 1161.95   273.4 1142.19   288.3 1134.13     338 1111.61
   362.8 1097.07   382.7 1093.28   432.5 1089.61   457.4 1084.97   457.5 1084.99
   472.5 1087.46   482.3 1088.73   497.2 1088.95   502.2 1090.66   526.9 1109.78
   556.6 1125.76   571.4 1132.29   596.1 1145.46   620.8 1156.36   665.3  1178.5
   724.7 1206.18     779 1235.38   813.6 1250.12   882.8 1275.57   922.4 1292.56
#Mann= 3 , 0 , 0
       0      .1       0   457.5    .045       0   472.5      .1       0
Bank Sta=457.5,472.5
XS Rating Curve= 0 ,0
Exp/Cntr=0.3,0.1

Type RM Length L Ch R = 1 ,7413.9  ,108.7,110.5,112
XS GIS Cut Line= 3
     1728925.487      208351.529     1729117.392      207938.895
     1729316.651      207521.409
#Sta/Elev= 30
       0 1247.34    54.4 1223.18   168.2 1177.11   178.1 1172.48   197.9 1165.11
   286.9  1125.8   306.7 1118.06   326.5 1105.04   331.4 1103.18   351.2 1102.13
   375.9 1098.85   405.6  1091.9   435.3  1087.4   446.2 1084.15   455.1 1081.64
   461.2 1083.06     475 1086.85   499.8 1086.31   524.7 1087.67   579.4 1092.14
   604.3 1095.63   644.1 1103.96   688.9 1117.26   748.6 1132.72   768.4 1140.51
   783.4 1143.44   808.2 1150.23     853  1158.1   872.9  1162.9   917.7 1169.31
#Mann= 3 , 0 , 0
       0      .1       0   446.2    .045       0   461.2      .1       0
Bank Sta=446.2,461.2
XS Rating Curve= 0 ,0
Exp/Cntr=0.3,0.1

Type RM Length L Ch R = 1 ,7303.4  ,259,277.3,295.6
XS GIS Cut Line= 4
     1728955.463      208386.958     1729184.627      208040.966
     1729305.949      207832.022     1729438.504      207685.987
#Sta/Elev= 30
       0 1261.13    59.3 1240.66   113.6 1223.96   133.4 1216.23   153.2 1209.96
   187.7 1194.89   222.3 1178.24   237.1 1169.86   271.7 1153.53   306.3 1138.19
     331 1130.19   370.5 1110.87   395.2  1102.2   405.1 1097.28   434.7 1091.14
   457.7 1082.65   464.3 1081.99   472.7 1083.77     484 1085.96   513.6 1087.84
   602.4 1089.77   636.9 1091.47   666.5 1095.06   710.8 1096.52   750.3 1100.25
   755.2 1100.45     770 1098.43   794.7 1102.31   819.3 1102.79   853.8 1104.77
#Mann= 3 , 0 , 0
       0      .1       0   457.7    .045       0   472.7      .1       0
Bank Sta=457.7,472.7
XS Rating Curve= 0 ,0
Exp/Cntr=0.3,0.1

Type RM Length L Ch R = 1 ,7026.2  ,402.4,406.3,410.1
XS GIS Cut Line= 4
     1728950.079      208430.138     1729306.827      208228.765
     1729453.211      208190.506     1729818.648      208088.296
#Sta/Elev= 30
       0 1275.91    74.9 1250.33   134.9 1224.42   234.8 1175.55   254.8 1163.89
   294.8 1143.99   304.8 1137.71   319.7 1125.12   364.7 1107.06   379.7 1099.43
   399.7 1087.01   409.7 1084.86   453.6  1083.9   468.2 1080.88     478 1080.46
   482.8 1081.14   497.8 1086.06   507.3 1087.51   541.4 1088.52   556.1 1094.66
   580.9  1109.7   585.9 1111.08   620.9 1113.51   630.9 1116.15   690.8 1152.44
   755.7 1185.59   810.6 1217.64   845.6 1234.22   855.5 1239.95   940.4 1278.55
#Mann= 3 , 0 , 0
       0      .1       0   482.8    .045       0   497.8      .1       0
Bank Sta=482.8,497.8
XS Rating Curve= 0 ,0
Exp/Cntr=0.3,0.1

Type RM Length L Ch R = 1 ,6619.9  ,144.6,147.4,150.3
XS GIS Cut Line= 4
     1728996.856      208571.882     1729339.896      208613.284
     1729511.416      208599.483     1729834.741      208565.968
#Sta/Elev= 30
       0 1265.69    49.4 1243.91   118.5 1204.82   128.3 1198.41   138.2 1194.09
   162.9 1179.09   207.3 1157.32   222.1  1148.1   241.9 1139.26   271.5 1123.41
   286.3 1117.57   330.7 1092.22   345.5 1088.47     375  1086.7   419.3 1086.28
   435.7 1082.27   443.9 1080.57   450.7 1082.68   468.4  1087.4   532.4 1090.67
   581.6 1101.29   616.1 1105.43   660.4 1108.82   699.8 1108.14   739.2  1114.2
   768.8  1115.4   788.5 1117.53   803.3 1117.93     823 1115.83   842.7 1116.01
#Mann= 3 , 0 , 0
       0      .1       0   435.7    .045       0   450.7      .1       0
Bank Sta=435.7,450.7
XS Rating Curve= 0 ,0
Exp/Cntr=0.3,0.1

Type RM Length L Ch R = 1 ,6472.5  ,471.8,470.2,468.7
XS GIS Cut Line= 4
     1728969.577      208605.683     1729298.495      208739.459
     1729584.361      208761.146     1729849.158      208887.368
#Sta/Elev= 30
       0 1273.36      69 1247.05   108.5 1228.79   152.9 1207.06   167.7 1198.17
   187.4 1190.73     217 1174.42   256.4  1156.8   310.7 1120.92   335.4  1110.9
   355.1 1108.55     360 1106.64   369.9 1101.61   394.6 1085.29   414.4  1082.8
   434.2 1083.26     458 1081.51   468.8  1080.6     473 1081.17   488.5 1084.77
   572.6 1087.01   592.3 1093.93   612.1 1095.73   626.9  1100.1   671.6 1109.34
   706.4 1125.19   726.3 1136.27   756.1 1148.69   890.4 1202.32   935.1 1217.44
#Mann= 3 , 0 , 0
       0      .1       0     458    .045       0     473      .1       0
Bank Sta=458,473
XS Rating Curve= 0 ,0
Exp/Cntr=0.3,0.1

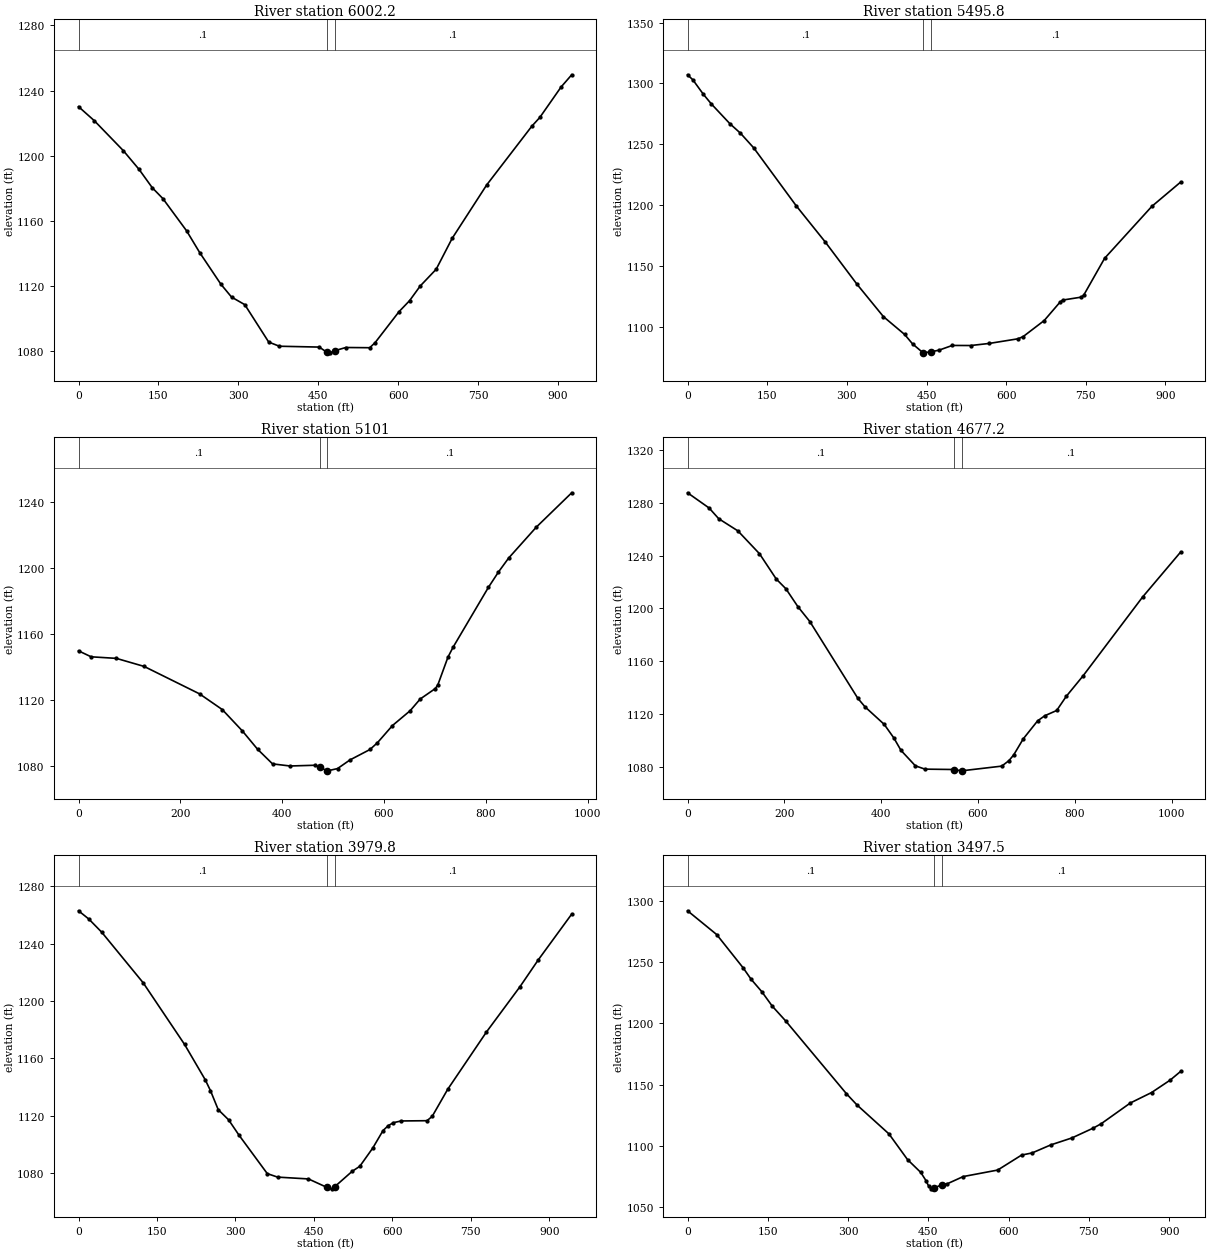
Type RM Length L Ch R = 1 ,6002.2  ,502.4,506.5,510.5
XS GIS Cut Line= 3
     1728916.193      209138.781     1729168.376      209210.647
     1729831.743      209197.291
#Sta/Elev= 30
       0 1230.09    29.7 1221.44    84.1 1203.04   113.8 1191.45   138.5  1180.2
   158.3 1173.57   202.8 1153.76   227.6 1140.27   267.2 1120.91   287.2 1112.99
   312.1 1108.32     357 1085.31     377 1082.76   451.8 1082.24   465.9 1079.13
   471.8  1078.7   480.9 1080.01   501.7 1081.98   546.6 1081.85   556.6 1084.94
   601.5 1103.99   621.4 1110.79   641.4 1119.82   671.3  1130.1   701.2 1149.04
   766.1 1181.94   850.9  1218.1   865.9 1223.48   905.8  1242.2   925.7 1249.69
#Mann= 3 , 0 , 0
       0      .1       0   465.9    .045       0   480.9      .1       0
Bank Sta=465.9,480.9
XS Rating Curve= 0 ,0
Exp/Cntr=0.3,0.1

Type RM Length L Ch R = 1 ,5495.8  ,382,394.8,407.6
XS GIS Cut Line= 3
     1728770.514      209545.261     1729276.808      209630.575
     1729648.376      209816.227
#Sta/Elev= 30
       0 1307.11      10 1302.96    29.9    1291    44.9 1283.09    79.8 1266.86
    99.7 1259.04   124.6 1247.01   204.4 1199.52   259.2  1169.7     319 1134.93
   368.9 1108.24   408.8  1093.6   423.7 1085.86   443.6 1078.49   444.2 1078.51
   459.2  1079.4   473.6 1080.69   498.5 1084.57   533.2  1084.5   567.8  1086.2
   622.2 1090.03   632.1 1091.87   671.7 1105.07   701.3  1120.1   706.3 1121.87
   740.9 1124.25   745.8 1125.71   785.4 1156.21   874.4 1198.94   928.8 1218.96
#Mann= 3 , 0 , 0
       0      .1       0   444.2    .045       0   459.2      .1       0
Bank Sta=444.2,459.2
XS Rating Curve= 0 ,0
Exp/Cntr=0.3,0.1

Type RM Length L Ch R = 1 ,5101    ,441.2,423.8,405.1
XS GIS Cut Line= 4
     1728667.022      209906.109       1729028.4      209902.641
     1729225.549       210072.19     1729555.015       210181.21
#Sta/Elev= 30
       0  1149.9    24.8 1146.28    74.3 1145.33   128.7 1140.46   237.6 1123.82
   282.2 1114.31   321.8 1101.31   351.5 1090.26     381 1081.34   415.4 1080.06
   464.4 1080.51   473.6 1079.25   488.6 1077.13     489 1077.12   508.6 1078.49
   533.1 1083.74   572.4 1090.07   587.1  1094.2   616.5 1104.59   651.2 1113.57
     671 1120.69   700.8 1127.05   705.7 1129.33   725.5  1146.1   735.4 1152.02
   804.9 1188.39   824.7 1197.73   844.5 1206.11     899 1224.93   968.5 1245.76
#Mann= 3 , 0 , 0
       0      .1       0   473.6    .045       0   488.6      .1       0
Bank Sta=473.6,488.6
XS Rating Curve= 0 ,0
Exp/Cntr=0.3,0.1

Type RM Length L Ch R = 1 ,4677.2  ,705.5,697.4,687.8
XS GIS Cut Line= 4
     1728664.487      210653.143     1728943.626      210358.056
     1729215.692      210342.285     1729554.239      210374.193
#Sta/Elev= 30
       0  1287.5    44.6 1275.96    64.4 1267.87     104 1258.66   148.6 1241.37
   183.3  1222.2   203.1 1214.88   227.9 1201.33   252.6 1190.05   351.7 1131.98
   366.6 1125.49   406.2 1112.25     426 1102.03   440.9 1092.55   470.6 1080.86
   490.4 1078.36     551 1078.07   564.8 1077.07     566 1077.08     649 1080.64
   663.8 1084.77   673.8 1089.17   693.5  1101.3   723.1  1114.9   737.9 1118.76
   762.5 1122.74   782.2  1133.4   816.7 1148.81   939.9 1208.58  1018.8 1242.75
#Mann= 3 , 0 , 0
       0      .1       0     551    .045       0     566      .1       0
Bank Sta=551,566
XS Rating Curve= 0 ,0
Exp/Cntr=0.3,0.1

Type RM Length L Ch R = 1 ,3979.8  ,465.4,482.3,499.1
XS GIS Cut Line= 4
     1728776.624      211082.475     1729105.288      210990.906
     1729311.519      210925.987     1729633.648      210714.561
#Sta/Elev= 30
       0 1262.81    19.8 1257.03    44.5 1247.82   123.6 1212.64   202.7 1169.71
   242.3 1145.02   252.2 1137.51     267 1124.28   286.8 1117.21   306.6 1106.56
   360.8  1079.7   380.5 1077.26   439.5 1075.99   474.5 1070.16   483.7 1069.09
   489.5 1070.51     523 1081.27   537.7 1084.82   562.3 1097.44   582.1 1109.72
     592  1113.1   601.8 1115.18   616.7 1116.38   666.1 1116.56     676 1119.57
   705.6 1138.39   779.7 1178.34   843.9 1209.96   878.5 1228.47   942.7  1260.5
#Mann= 3 , 0 , 0
       0      .1       0   474.5    .045       0   489.5      .1       0
Bank Sta=474.5,489.5
XS Rating Curve= 0 ,0
Exp/Cntr=0.3,0.1

Type RM Length L Ch R = 1 ,3497.5  ,503.7,500.1,496.5
XS GIS Cut Line= 3
     1728765.987      211266.761     1729103.317       211365.49
     1729618.885      211608.754
#Sta/Elev= 30
       0 1291.88    54.4  1272.5     104 1245.26   118.8    1236   138.6 1225.96
   158.4 1214.03   183.2  1202.1     297 1142.61   316.8  1133.4   376.3  1109.9
     411 1088.96   435.8 1078.45   445.7 1071.65   450.6 1067.17   455.6 1065.07
   461.3 1065.91   476.3 1068.58   485.3  1069.2   515.1 1075.09   579.5 1080.39
   624.1 1092.59     644 1094.38   678.7  1100.9   718.3  1106.6     758  1114.6
   772.8 1118.14   827.4  1135.1     867 1143.61   901.7 1153.72   921.6 1160.94
#Mann= 3 , 0 , 0
       0      .1       0   461.3    .045       0   476.3      .1       0
Bank Sta=461.3,476.3
XS Rating Curve= 0 ,0
Exp/Cntr=0.3,0.1