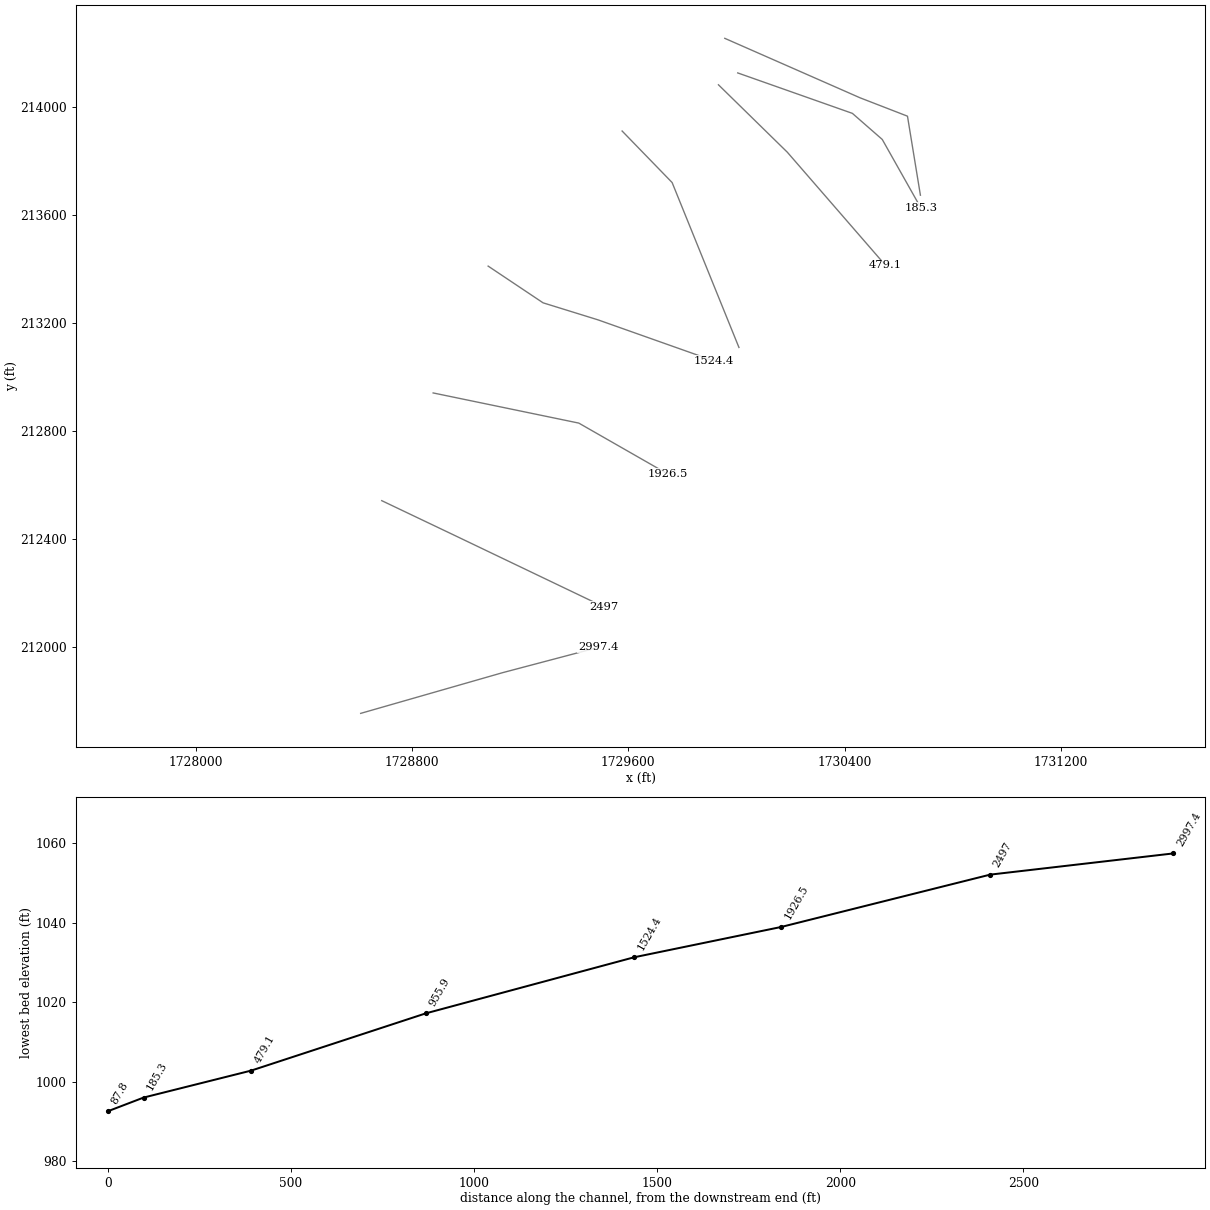
HEC-RAS study LitleCbCr1.prj: LitleCbCr1

--- LitleCbCr1.g01 (geometry) --- (continued)

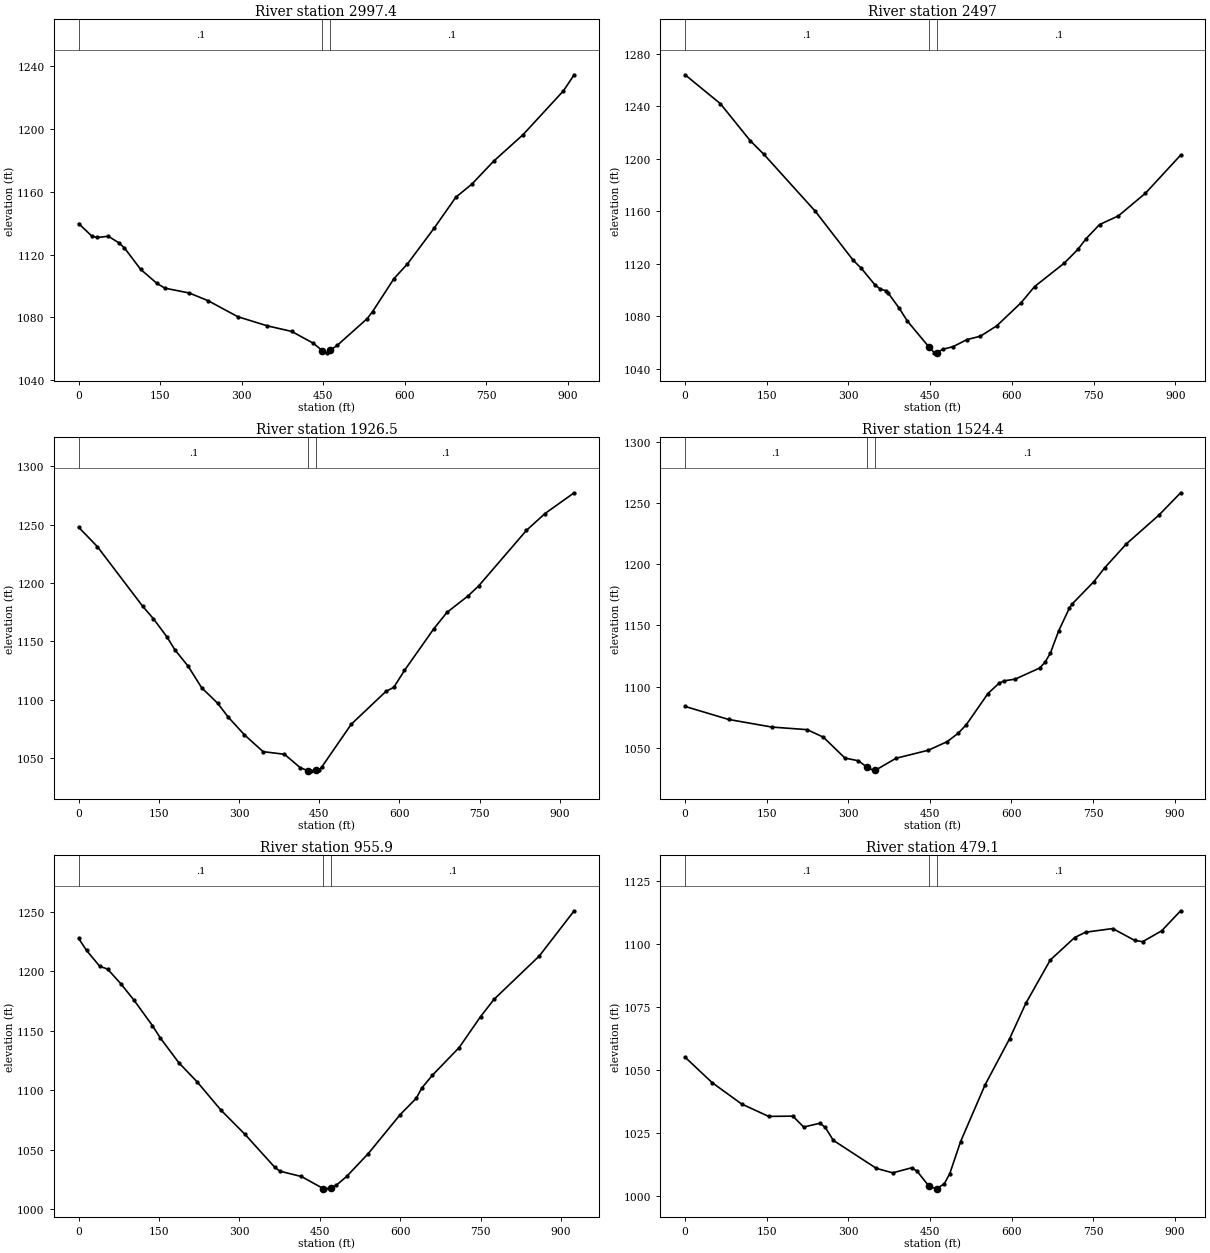
Type RM Length L Ch R = 1 ,2997.4  ,516.9,500.4,483.8
XS GIS Cut Line= 3
     1728610.454      211754.949     1729134.861       211905.68
     1729488.718      211999.351
#Sta/Elev= 30
       0 1139.78    24.8 1131.62    34.7  1130.9    54.6 1131.68    74.4  1127.4
    84.3 1124.24   114.1 1110.61   143.8 1101.74   158.7 1098.64   203.4 1095.57
   238.1 1090.68   292.7 1080.49   347.2 1074.64   391.9 1071.11   431.6 1063.62
   448.3 1058.87   456.4 1057.47   463.3 1059.18   476.2 1062.36   530.8 1079.22
   540.7 1083.67   580.3 1104.77     605 1114.09   654.5 1137.05     694 1156.53
   723.7 1164.95   763.3 1179.38   817.7 1196.36   891.9 1224.23   911.7 1234.47
#Mann= 3 , 0 , 0
       0      .1       0   448.3    .045       0   463.3      .1       0
Bank Sta=448.3,463.3
XS Rating Curve= 0 ,0
Exp/Cntr=0.3,0.1

Type RM Length L Ch R = 1 ,2497    ,565,570.5,576
XS GIS Cut Line= 3
     1728688.264      212542.999     1728953.483      212416.297
     1729508.933      212149.804
#Sta/Elev= 30
       0 1263.86    64.8 1241.84   119.6 1213.66   144.5 1203.37   239.1 1159.93
   308.8 1122.57   323.7 1116.44   348.6 1103.92   358.5 1100.64   368.4  1099.5
   373.4 1097.35   393.3 1086.07   408.2  1076.3   447.5 1056.76   457.9 1052.13
   462.5 1052.33   472.8 1054.74   492.7 1056.95   517.5  1062.2   542.4 1064.81
   572.2 1072.66   616.9 1090.25   641.7 1102.54   696.4 1120.49   721.2 1130.83
   736.1 1138.92     761  1149.8   795.7 1156.41   845.4 1173.68     910  1202.7
#Mann= 3 , 0 , 0
       0      .1       0   447.5    .045       0   462.5      .1       0
Bank Sta=447.5,462.5
XS Rating Curve= 0 ,0
Exp/Cntr=0.3,0.1

Type RM Length L Ch R = 1 ,1926.5  ,404.8,402.1,399.4
XS GIS Cut Line= 3
     1728878.332      212942.036     1729416.784      212830.311
      1729743.79       212642.84
#Sta/Elev= 30
       0 1247.68      35 1231.09     120 1179.85     140 1169.23     165 1153.84
     180 1142.68     205 1128.49     230 1110.23     260 1096.86     280 1084.91
     310 1069.86     345  1055.4     385 1053.15   414.9 1041.49   429.8 1039.05
   434.9 1038.96   444.8 1039.27   449.9 1039.75   454.9 1042.34   509.9  1078.9
   574.7    1107   589.6 1110.58   609.4 1124.99     664 1160.51   688.8 1174.68
   728.5 1188.92   748.3 1197.47   837.6 1245.02   872.3 1259.45   926.8 1277.21
#Mann= 3 , 0 , 0
       0      .1       0   429.8    .045       0   444.8      .1       0
Bank Sta=429.8,444.8
XS Rating Curve= 0 ,0
Exp/Cntr=0.3,0.1

Type RM Length L Ch R = 1 ,1524.4  ,588.8,568.6,548.3
XS GIS Cut Line= 4
      1729081.63      213411.902     1729284.694      213275.869
     1729487.758      213212.781     1729915.573      213060.976
#Sta/Elev= 30
       0  1083.9    79.8 1073.29   159.6 1067.05   224.5 1064.94   254.3 1058.77
   293.9 1041.73   318.6 1039.56   334.9 1034.12   348.3 1031.32   349.9 1031.81
   387.8 1041.59   447.2 1048.15     482  1055.2     502 1061.99   516.9 1068.94
   556.8 1094.44   576.8 1102.72   586.8 1104.83   606.7 1106.16   651.6 1115.21
   661.6 1119.88   671.6 1127.51   686.5 1145.28   706.5 1164.27   711.5  1167.5
   751.4 1185.74   771.3 1197.01   811.2  1216.6   871.1 1240.11     911 1258.33
#Mann= 3 , 0 , 0
       0      .1       0   334.9    .045       0   349.9      .1       0
Bank Sta=334.9,349.9
XS Rating Curve= 0 ,0
Exp/Cntr=0.3,0.1

Type RM Length L Ch R = 1 ,955.9   ,469.3,476.7,484.2
XS GIS Cut Line= 3
     1729576.894      213912.351     1729761.796      213721.426
     1730008.787      213110.509
#Sta/Elev= 30
       0 1227.37    14.8 1217.34    39.4 1204.02    54.1 1201.65    78.8 1189.33
   103.4 1175.53   137.8 1154.15   152.6 1143.75     187 1123.07   221.5 1106.83
   265.8 1083.16   310.7 1062.84   365.6  1035.5   375.6 1032.02   415.6 1027.57
   456.8 1017.35   460.5 1017.21   471.8 1018.23   480.4 1020.06   500.4 1027.74
   540.4 1046.78   600.2  1079.6   630.2 1093.31   640.2 1101.74   660.2  1112.6
   710.1 1135.83     750 1161.74     775 1176.23   859.8 1212.76   924.7 1250.62
#Mann= 3 , 0 , 0
       0      .1       0   456.8    .045       0   471.8      .1       0
Bank Sta=456.8,471.8
XS Rating Curve= 0 ,0
Exp/Cntr=0.3,0.1

Type RM Length L Ch R = 1 ,479.1   ,290.4,293.8,297.2
XS GIS Cut Line= 3
     1729933.066      214083.569     1730187.639      213833.802
     1730550.422       213414.86
#Sta/Elev= 30
       0 1055.03    49.5 1044.97     104 1036.45   153.6 1031.55   198.1 1031.65
     218 1027.32   247.7 1028.83   257.6 1027.21   272.4 1022.05   351.7 1010.91
   381.6 1009.16   416.6 1011.17   426.5 1009.78   447.9 1003.96   461.5 1002.81
   462.9 1002.86   476.5 1004.88   486.4  1008.8   506.4 1021.58   551.4 1044.08
   596.3 1062.31   626.2 1076.38   671.2 1093.58   716.1 1102.51   736.1 1104.61
     786 1106.06     826 1101.39   840.9 1100.84   875.9 1105.16   910.8 1113.11
#Mann= 3 , 0 , 0
       0      .1       0   447.9    .045       0   462.9      .1       0
Bank Sta=447.9,462.9
XS Rating Curve= 0 ,0
Exp/Cntr=0.3,0.1

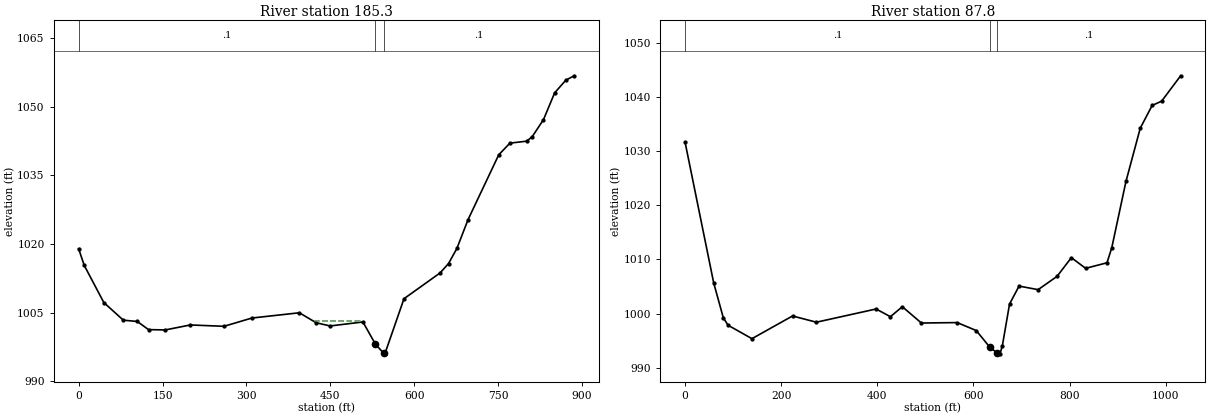
Type RM Length L Ch R = 1 ,185.3   ,89.6,97.5,105.4
XS GIS Cut Line= 4
      1730004.29      214127.554     1730428.161      213977.721
     1730538.565      213881.117     1730680.513      213628.766
#Sta/Elev= 30
       0 1018.98      10 1015.34      45 1007.23    79.9 1003.37   104.9 1003.09
   124.9 1001.31   154.8 1001.24   199.8 1002.33   259.8 1002.03   309.7 1003.84
   394.6 1004.99   424.6 1002.81   449.6 1002.11   508.2 1002.98   530.2   998.2
   545.2  996.14   547.4  996.02   581.6 1008.06   646.2  1013.7   661.2 1015.74
   676.2 1019.05   696.1 1025.33     751  1039.5     771 1042.04     801 1042.47
   810.9 1043.47   830.9 1047.16   850.9 1053.02   870.8 1055.78   885.8 1056.75
#Mann= 3 , 0 , 0
       0      .1       0   530.2    .045       0   545.2      .1       0
#XS Ineff= 2 ,-1
   43.36  394.111004.938   420.1  503.58 1003.12
Permanent Ineff=
       F       F
Bank Sta=530.2,545.2
XS Rating Curve= 0 ,0
Exp/Cntr=0.3,0.1

Type RM Length L Ch R = 1 ,87.8    ,78.2,87.8,97.4
XS GIS Cut Line= 4
     1729956.463      214255.692      1730456.45      214035.408
     1730631.807      213967.294     1730679.632      213674.548
#Sta/Elev= 30
       0 1031.63    59.6 1005.64    79.5  999.24    89.4  997.86   139.1  995.38
   223.5  999.57   273.2  998.42   397.4 1000.86   427.2  999.44     452 1001.28
   491.7  998.27   566.2  998.35   605.8  996.88   634.2  993.79   649.2  992.76
   655.3  992.58   660.2   994.1   675.1 1001.78   694.9 1005.09   734.5 1004.43
     774 1006.89   803.7 1010.34   833.4 1008.37   877.8 1009.39   887.7 1012.12
   917.4 1024.44   947.1 1034.25   971.8 1038.44   991.6 1039.24  1031.1 1043.92
#Mann= 3 , 0 , 0
       0      .1       0   634.2    .045       0   649.2      .1       0
#XS Ineff= 2 , 0
          451.73 1001.16
Permanent Ineff=
       F       F
Bank Sta=634.2,649.2
XS Rating Curve= 0 ,0
Exp/Cntr=0.3,0.1

Chan Stop Cuts=-1
Use User Specified Reach Order=0